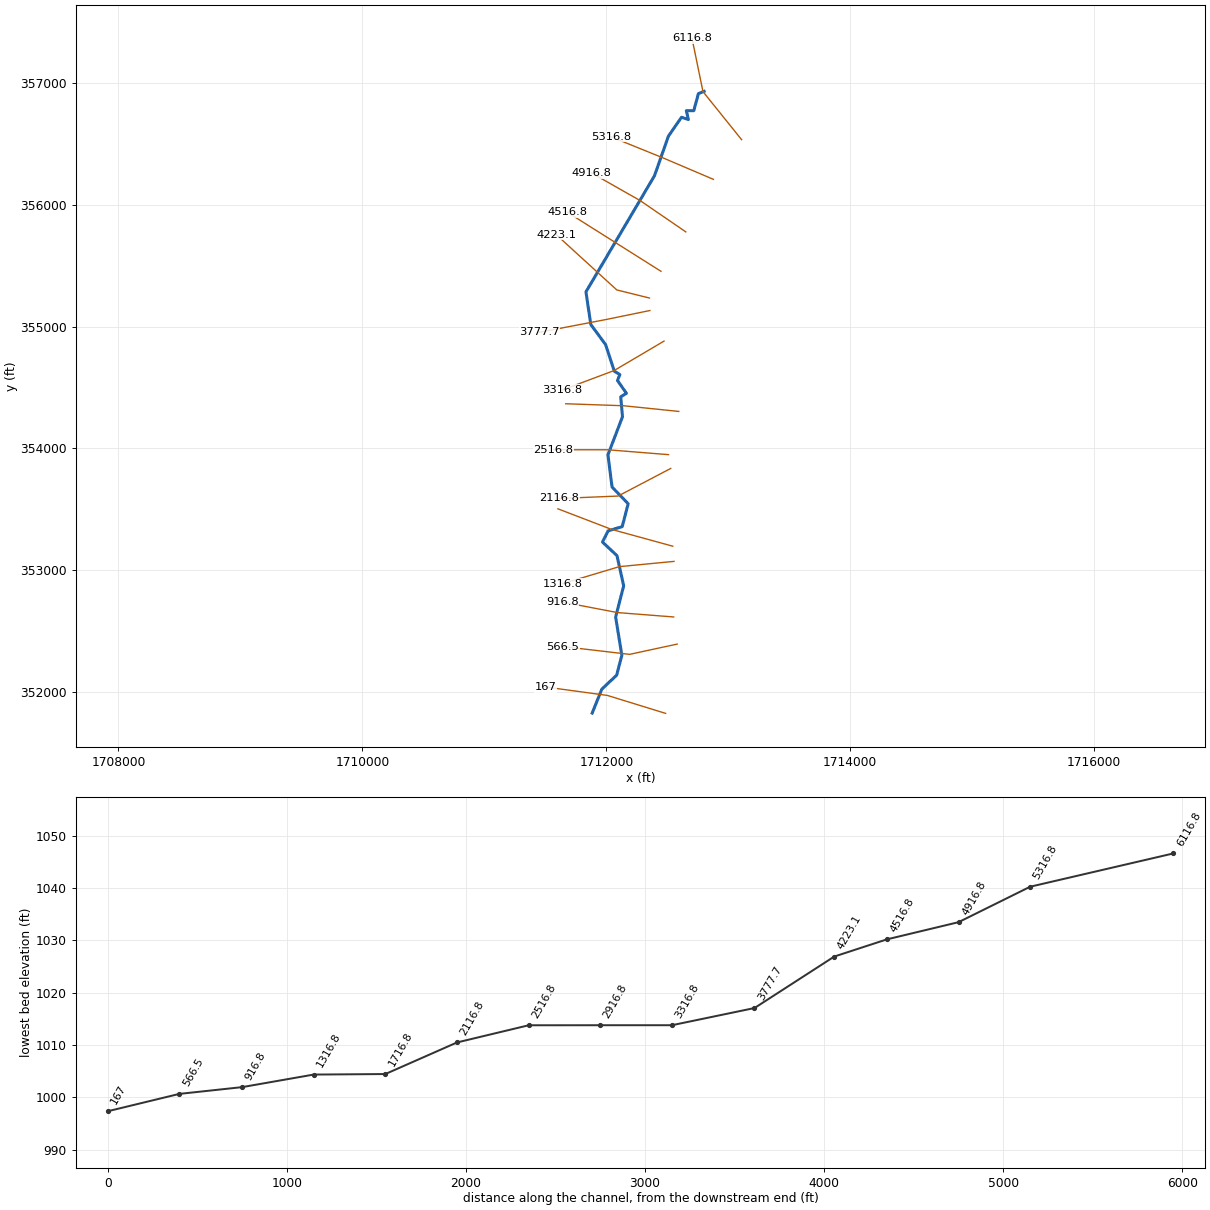
--- LckRn1.prj (project) ---

Proj Title=LckRn1
Current Plan=p01
Default Exp/Contr=0,0
English Units
Geom File=g01
Flow File=f01
Plan File=p01
BEGIN DESCRIPTION:
END DESCRIPTION:
DSS Export Rating Curves= 0
DSS Export Rating Curve Sorted= 0
DSS Export Volume Flow Curves= 0
DXF OffsetX= 0
DXF OffsetY= 0
DXF ScaleX= 0
DXF ScaleY= 0

--- LckRn1.p01 (plan) ---

Plan Title=Floodplain
Program Version=4.00
Geom File=g01
Flow File=f01
K Sum by GR=0
Std Step Tol=0.01
Critical Tol=0.01
Num of Std Step Trials=20
Max Error Tol=0.3
Flow Tol Ratio=0.001
Split Flow NTrial=30
Split Flow Tol=0.02
Split Flow Ratio=0.02
Log Output Level=0
Friction Slope Method=1
Unsteady Friction Slope Method=2
Unsteady Bridges Friction Slope Method=1
Global Log Level=0
CheckData=False
Run HTab=0
Run UNet=0
Run PostProcess=0
UNET Theta=0
UNET Theta Warmup=0
UNET ZTol=0
UNET ZSATol=0
UNET MxIter=0
UNET MaxInSteps=0
UNET DtIC=0
UNET DtMin=0
UNET MaxCRTS=0
UNET WFStab=0
UNET SFStab=0
UNET WFX=0
UNET SFX=0
UNET DSS MLevel=0
UNET DZMax Abort=0
UNET Convert EG Bridges=0
UNET Use Existing IB Tables=0
UNET Froude Limit=0
UNET Froude Power=0
Write IC File=0
Echo Input=False
Echo Output=False
Write Detailed=0

--- LckRn1.f01 (steady flow) ---

Flow Title=NFF Regression Equation
Program Version=4.00
Number of Profiles=1
Profile Names=P100yr
River Rch & RM=LckRn1,Main      ,6116.8
637.0555
River Rch & RM=LckRn1,Main      ,4223.1
691.5380
River Rch & RM=LckRn1,Main      ,3777.7
1184.141
River Rch & RM=LckRn1,Main      ,167
1247.221
Boundary for River Rch & Prof#=LckRn1,Main      ,1
Up Type=0
Dn Type=3
Dn Slope=0.005968

--- LckRn1.g01 (geometry) ---

Geom Title=USGS 3m DEM
Program Version=4.00

River Reach=LckRn1     ,Main
Reach XY= 30
     1712801.903      356932.502     1712754.911      356913.680
     1712716.721      356772.889     1712655.874      356773.869
     1712672.692      356700.669     1712616.093      356719.314
     1712509.144      356564.684     1712394.691      356238.851
     1711832.959      355285.179     1711872.690      355016.408
     1711993.701      354852.452     1712065.267      354633.369
     1712110.610      354605.677     1712091.466      354556.471
     1712164.715      354452.169     1712118.083      354422.536
     1712132.374      354258.562     1712013.126      353946.701
     1712046.935      353681.592     1712178.920      353544.394
     1712130.213      353356.571     1712014.898      353321.710
     1711968.154      353229.856     1712087.100      353118.191
     1712142.149      352870.455     1712076.223      352613.499
     1712127.141      352298.819     1712084.460      352136.153
     1711963.077      352021.301     1711883.984      351824.686

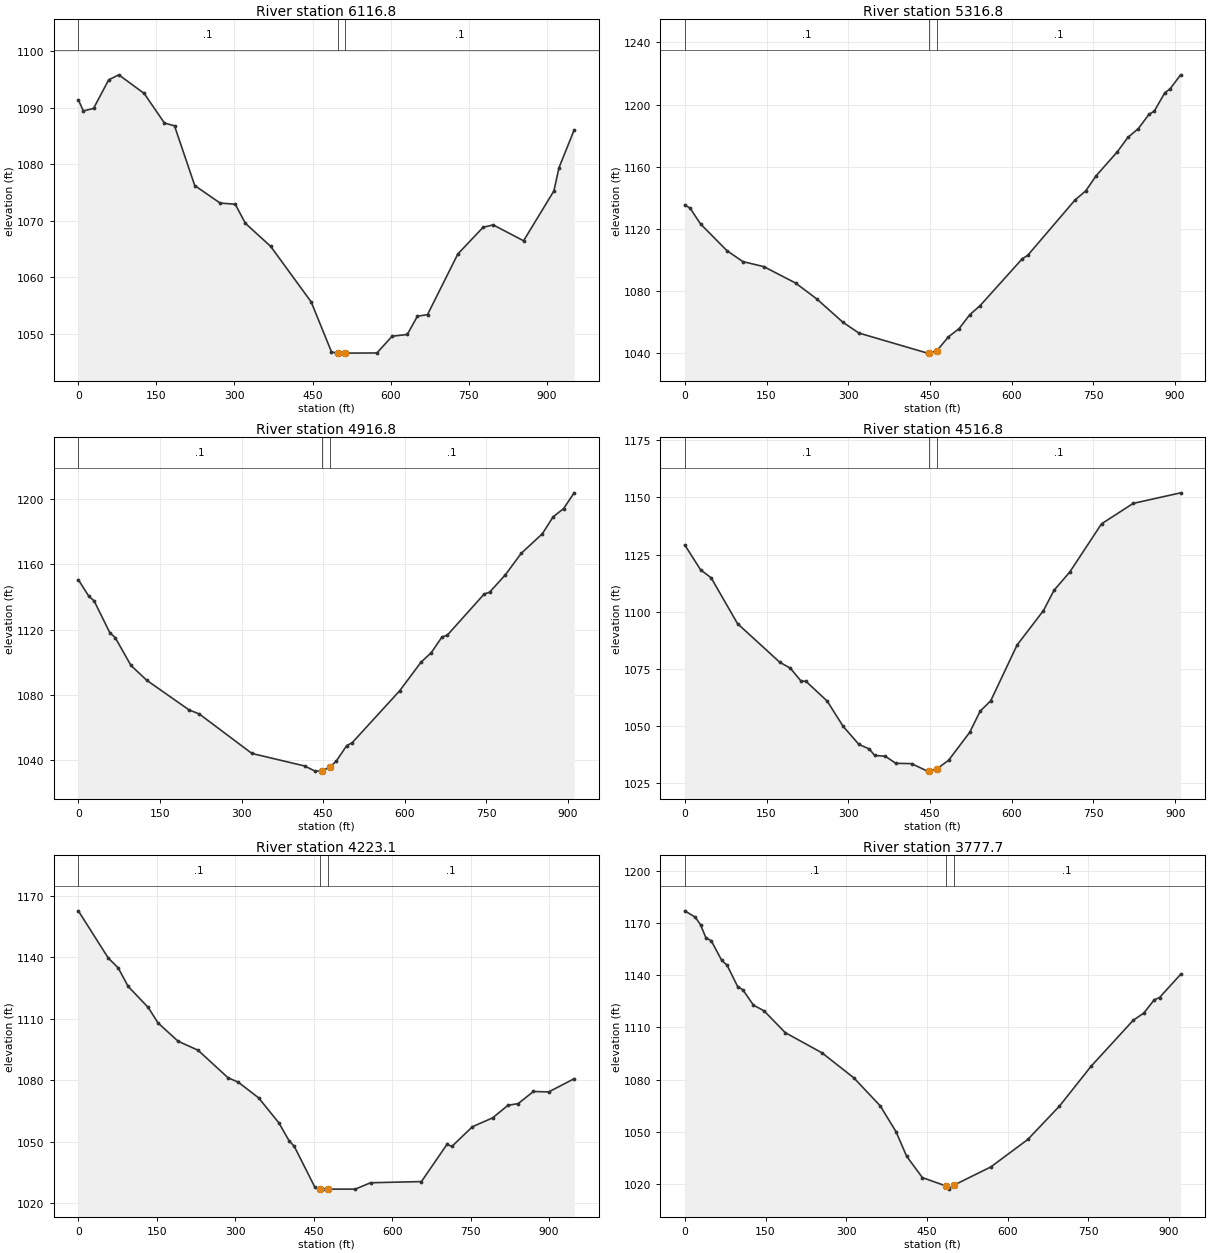
Type RM Length L Ch R = 1 ,6116.8,731.439,800,740.338
XS GIS Cut Line= 3
     1713108.797      356535.402     1712792.245      356929.910
     1712702.317      357367.757
#Sta/Elev= 30
       0 1091.39     9.7 1089.42    29.2 1089.87    58.4 1094.93    77.8 1095.81
   126.5 1092.52   165.4 1087.29   184.8 1086.79   223.7 1076.23   272.4 1073.13
   301.5 1072.93   321.0 1069.55   369.6 1065.47   447.4 1055.66   486.4 1046.83
   496.1 1046.59   498.3 1046.59   513.3 1046.59   573.8 1046.62   603.0 1049.58
   632.1 1049.89   651.6 1053.12   671.0 1053.40   729.3 1064.13   777.9 1068.85
   797.3 1069.27   855.6 1066.46   913.9 1075.28   923.6 1079.37   952.8 1086.06
#Mann= 3 , 0 , 0
       0     0.1       0   498.3   0.045       0   513.3     0.1       0
Bank Sta=   498.3,   513.3
Exp/Cntr=0.3,0.1

Type RM Length L Ch R = 1 ,5316.8,404.416,400,397.087
XS GIS Cut Line= 3
     1712877.866      356209.310     1712459.382      356387.867
     1712037.690      356558.982
#Sta/Elev= 30
       0 1135.48     9.7 1133.42    29.0 1123.22    77.4 1106.08   106.5 1099.08
   145.2 1095.80   203.3 1085.30   242.0 1075.13   290.4 1060.02   319.5 1053.15
   445.3 1040.23   447.5 1040.29   462.5 1041.66   484.0 1050.73   503.4 1055.95
   522.8 1064.80   542.1 1070.78   619.6 1100.96   629.3 1103.04   716.4 1138.71
   735.8 1144.48   755.1 1154.27   793.9 1169.63   813.2 1178.87   832.6 1184.59
   852.0 1193.73   861.7 1195.77   881.0 1207.53   890.7 1210.09   910.1 1219.12
#Mann= 3 , 0 , 0
       0     0.1       0   447.5   0.045       0   462.5     0.1       0
Bank Sta=   447.5,   462.5
Exp/Cntr=0.3,0.1

Type RM Length L Ch R = 1 ,4916.8,399.137,400,398.96
XS GIS Cut Line= 3
     1712651.634      355777.599     1712276.890      356035.038
     1711879.762      356261.122
#Sta/Elev= 30
       0 1150.45    19.3 1140.31    29.0 1137.52    58.0 1117.97    67.7 1115.12
    96.7 1098.07   125.8 1088.97   203.1 1070.98   222.5 1068.35   319.2 1044.25
   416.0 1036.62   435.3 1033.46   447.2 1033.57   462.2 1035.88   474.1 1039.51
   493.5 1049.12   503.3 1050.75   590.8 1082.56   629.7 1099.88   649.1 1105.95
   668.6 1115.44   678.3 1116.52   746.3 1141.74   756.1 1142.77   785.2 1153.47
   814.4 1166.60   853.3 1178.57   872.7 1188.79   892.2 1193.90   911.6 1203.53
#Mann= 3 , 0 , 0
       0     0.1       0   447.2   0.045       0   462.2     0.1       0
Bank Sta=   447.2,   462.2
Exp/Cntr=0.3,0.1

Type RM Length L Ch R = 1 ,4516.8,297.813,293.684,289.555
XS GIS Cut Line= 3
     1712447.750      355454.116     1712063.121      355697.191
     1711678.492      355940.266
#Sta/Elev= 30
       0 1129.16    29.0 1118.31    48.4 1114.79    96.8 1094.73   174.3 1077.84
   193.6 1075.26   213.0 1069.70   222.7 1069.43   261.4 1060.83   290.4 1049.85
   319.5 1041.89   338.8 1039.85   348.5 1037.03   367.9 1036.71   387.2 1033.61
   416.3 1033.45   445.3 1030.18   447.5 1030.18   462.5 1031.15   484.0 1034.89
   522.8 1047.14   542.1 1056.42   561.5 1060.98   609.9 1085.40   658.3 1100.48
   677.7 1109.35   706.7 1117.38   764.8 1138.42   822.9 1147.37   910.0 1152.00
#Mann= 3 , 0 , 0
       0     0.1       0   447.5   0.045       0   462.5     0.1       0
Bank Sta=   447.5,   462.5
Exp/Cntr=0.3,0.1

Type RM Length L Ch R = 1 ,4223.1,421.889,445.418,468.422
XS GIS Cut Line= 3
     1712353.821      355234.261     1712085.519      355300.971
     1711590.070      355754.254
#Sta/Elev= 30
       0 1162.71    57.2 1139.69    76.3 1134.83    95.3 1125.80   133.5 1115.60
   152.5 1107.96   190.7 1099.08   228.8 1094.69   286.2 1081.26   305.7 1079.10
   344.6 1071.47   383.5 1059.22   403.0 1050.47   412.7 1047.86   451.6 1028.17
   461.4 1027.00   471.1 1026.90   476.4 1026.90   529.5 1026.90   558.7 1030.01
   656.0 1030.59   704.7 1048.69   714.4 1047.77   753.3 1057.33   792.3 1061.70
   821.5 1067.83   840.9 1068.62   870.1 1074.55   899.3 1074.34   948.0 1080.78
#Mann= 3 , 0 , 0
       0     0.1       0   461.4   0.045       0   476.4     0.1       0
Bank Sta=   461.4,   476.4
Exp/Cntr=0.3,0.1

Type RM Length L Ch R = 1 ,3777.7,458.264,460.898,466.122
XS GIS Cut Line= 3
     1712356.951      355131.654     1712001.187      355058.518
     1711453.031      354953.103
#Sta/Elev= 30
       0 1176.91    19.6 1173.22    29.4 1168.82    39.3 1161.34    49.1 1159.76
    68.7 1148.41    78.5 1145.73    98.2 1133.43   108.0 1131.50   127.6 1122.74
   147.2 1119.50   186.5 1106.99   255.2 1095.30   314.1 1080.99   363.2 1064.89
   392.6 1050.03   412.2 1035.99   441.5 1023.70   484.7 1018.95   490.5 1017.07
   499.7 1019.29   568.9 1029.85   637.4 1045.61   696.2 1064.74   754.9 1087.60
   833.3 1114.05   852.9 1118.17   872.4 1125.81   882.2 1127.10   921.4 1140.44
#Mann= 3 , 0 , 0
       0     0.1       0   484.7   0.045       0   499.7     0.1       0
Bank Sta=   484.7,   499.7
Exp/Cntr=0.3,0.1

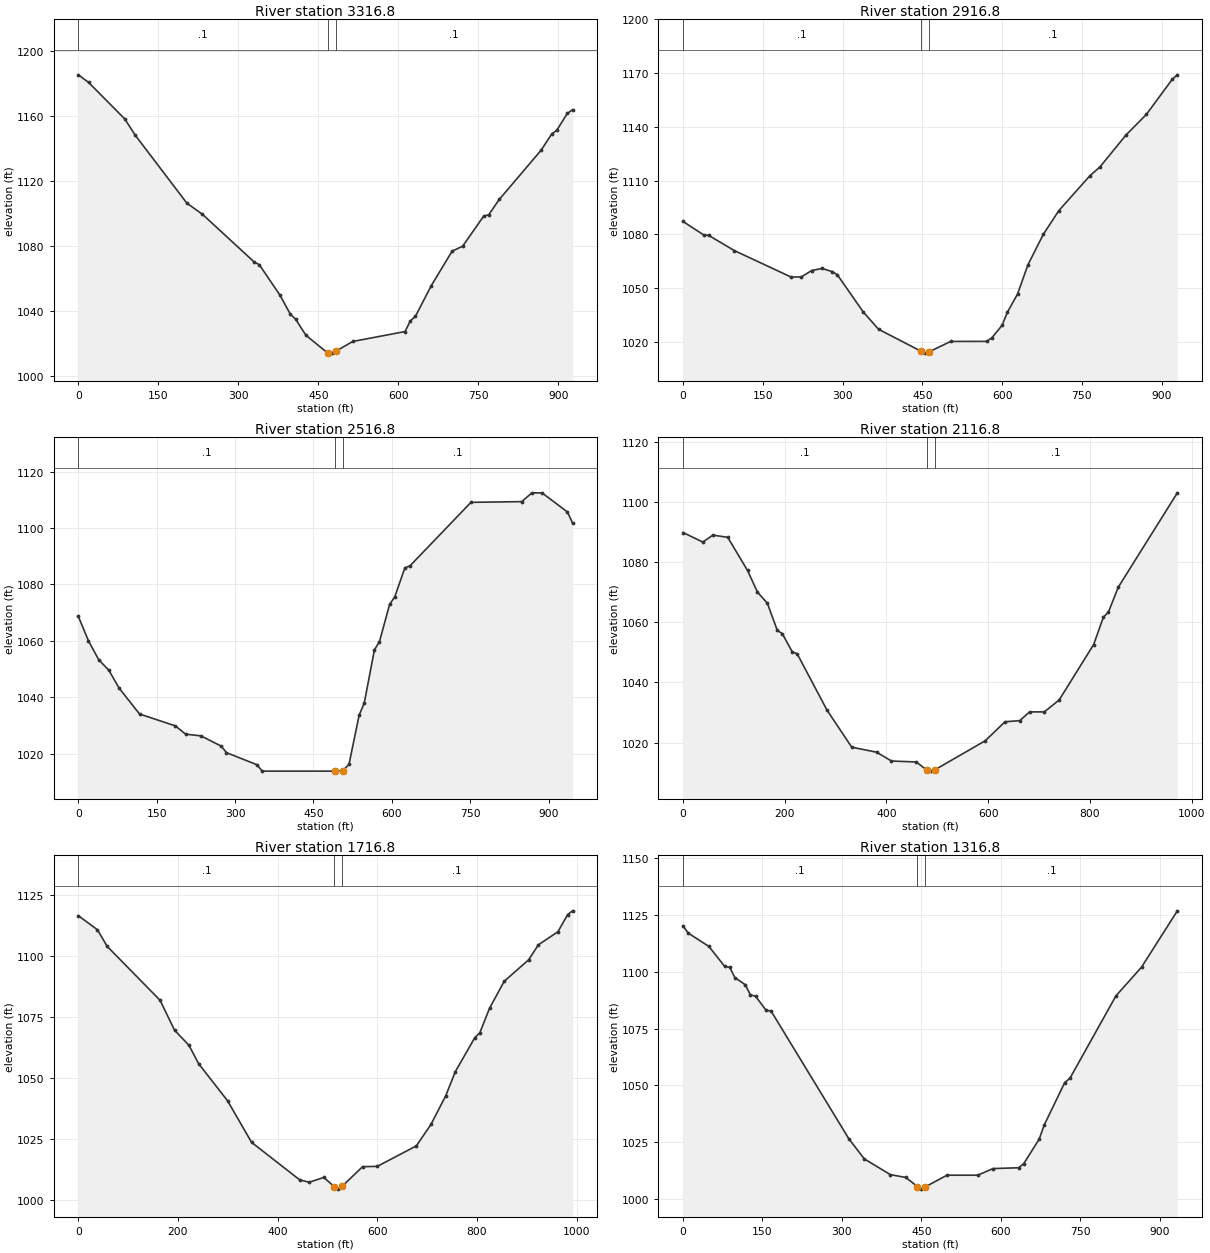
Type RM Length L Ch R = 1 ,3316.8,411.6,400,383.487
XS GIS Cut Line= 3
     1712472.545      354880.277     1712063.527      354638.473
     1711641.094      354479.592
#Sta/Elev= 30
       0 1185.09    19.4 1180.42    87.3 1157.89   106.7 1147.98   203.6 1106.09
   232.7 1099.27   329.7 1069.90   339.4 1068.21   378.2 1049.40   397.6 1037.71
   407.3 1034.73   426.7 1024.78   467.6 1013.85   475.1 1013.79   482.6 1014.93
   514.4 1020.96   612.5 1027.07   622.3 1033.51   632.1 1036.51   661.6 1055.28
   700.8 1076.59   720.4 1079.58   759.7 1098.00   769.5 1099.04   789.1 1108.38
   867.6 1138.72   887.2 1148.55   897.0 1151.01   916.7 1161.34   926.5 1163.59
#Mann= 3 , 0 , 0
       0     0.1       0   467.6   0.045       0   482.6     0.1       0
Bank Sta=   467.6,   482.6
Exp/Cntr=0.3,0.1

Type RM Length L Ch R = 1 ,2916.8,398.365,400,404.404
XS GIS Cut Line= 3
     1712593.985      354302.769     1712141.743      354349.407
     1711667.309      354365.800
#Sta/Elev= 30
       0 1087.22    38.7 1079.72    48.4 1079.41    96.7 1070.93   203.1 1056.22
   222.5 1056.28   241.8 1059.85   261.2 1061.01   280.5 1059.24   290.2 1057.45
   338.6 1036.82   367.6 1027.10   447.1 1014.91   454.6 1013.79   462.1 1014.44
   503.1 1020.30   570.9 1020.34   580.6 1022.34   600.0 1029.33   609.7 1036.53
   629.0 1046.77   648.4 1063.01   677.5 1080.06   706.5 1093.23   764.7 1112.62
   784.0 1117.64   832.5 1135.29   871.2 1146.91   919.7 1166.41   929.4 1168.97
#Mann= 3 , 0 , 0
       0     0.1       0   447.1   0.045       0   462.1     0.1       0
Bank Sta=   447.1,   462.1
Exp/Cntr=0.3,0.1

Type RM Length L Ch R = 1 ,2516.8,388.83,400,395.576
XS GIS Cut Line= 3
     1712510.156      353947.622     1712013.134      353987.728
     1711565.835      353987.818
#Sta/Elev= 30
       0 1068.70    19.6 1059.94    39.1 1053.29    58.7 1049.51    78.2 1043.20
   117.3 1034.03   185.8 1029.82   205.3 1026.90   234.7 1026.28   273.8 1022.62
   283.5 1020.34   342.2 1016.03   352.0 1013.78   491.1 1013.78   506.1 1013.88
   518.1 1016.20   537.5 1033.62   547.3 1037.91   566.7 1056.75   576.4 1059.70
   595.9 1072.94   605.6 1075.53   625.0 1085.85   634.8 1086.55   751.5 1109.07
   848.7 1109.32   868.1 1112.44   887.6 1112.41   936.2 1105.64   945.9 1101.70
#Mann= 3 , 0 , 0
       0     0.1       0   491.1   0.045       0   506.1     0.1       0
Bank Sta=   491.1,   506.1
Exp/Cntr=0.3,0.1

Type RM Length L Ch R = 1 ,2116.8,394.513,400,399.832
XS GIS Cut Line= 3
     1712527.843      353834.443     1712096.087      353607.565
     1711612.356      353587.692
#Sta/Elev= 30
       0 1089.76    39.0 1086.58    58.5 1088.89    87.8 1088.18   126.8 1077.16
   146.3 1069.96   165.8 1066.28   185.3 1057.26   195.1 1056.18   214.6 1050.16
   224.4 1049.48   282.9 1030.81   331.7 1018.45   380.4 1016.80   409.7 1013.86
   458.5 1013.54   480.2 1010.75   487.7 1010.50   495.2 1010.94   594.2 1020.59
   633.0 1026.90   662.0 1027.27   681.4 1030.18   710.4 1030.18   739.5 1034.14
   807.3 1052.54   826.6 1061.70   836.3 1063.29   855.7 1071.59   971.9 1102.95
#Mann= 3 , 0 , 0
       0     0.1       0   480.2   0.045       0   495.2     0.1       0
Bank Sta=   480.2,   495.2
Exp/Cntr=0.3,0.1

Type RM Length L Ch R = 1 ,1716.8,413.627,400,410.293
XS GIS Cut Line= 3
     1712544.463      353195.616     1712041.548      353334.113
     1711602.654      353502.867
#Sta/Elev= 30
       0 1116.39    38.6 1110.60    58.0 1103.82   164.2 1081.75   193.2 1069.53
   222.2 1063.31   241.5 1055.82   299.5 1040.66   347.8 1023.62   444.4 1008.25
   463.7 1007.29   492.7 1009.26   514.1 1005.44   521.6 1004.47   529.1 1005.55
   570.6 1013.66   600.0 1013.78   678.4 1022.16   707.8 1030.95   737.2 1042.59
   756.7 1052.57   795.9 1066.51   805.7 1068.38   825.3 1078.49   854.7 1089.52
   903.7 1098.31   923.3 1104.45   962.5 1109.79   982.1 1116.85   991.9 1118.36
#Mann= 3 , 0 , 0
       0     0.1       0   514.1   0.045       0   529.1     0.1       0
Bank Sta=   514.1,   529.1
Exp/Cntr=0.3,0.1

Type RM Length L Ch R = 1 ,1316.8,403.36,400,389.501
XS GIS Cut Line= 3
     1712554.790      353070.887     1712106.671      353027.680
     1711643.696      352888.732
#Sta/Elev= 30
       0 1120.17     9.8 1117.02    48.9 1111.15    78.3 1102.47    88.1 1101.94
    97.9 1097.45   117.4 1094.32   127.2 1089.87   137.0 1089.26   156.6 1083.14
   166.4 1082.68   313.2 1026.50   342.5 1017.64   391.5 1010.76   420.8 1009.49
   442.7 1005.51   450.2 1004.37   457.7 1005.38   498.5 1010.50   556.5 1010.50
   585.5 1013.41   633.9 1013.78   643.5 1015.60   672.6 1026.37   682.2 1032.61
   720.9 1051.28   730.6 1053.10   817.6 1089.41   865.9 1102.03   933.6 1126.83
#Mann= 3 , 0 , 0
       0     0.1       0   442.7   0.045       0   457.7     0.1       0
Bank Sta=   442.7,   457.7
Exp/Cntr=0.3,0.1

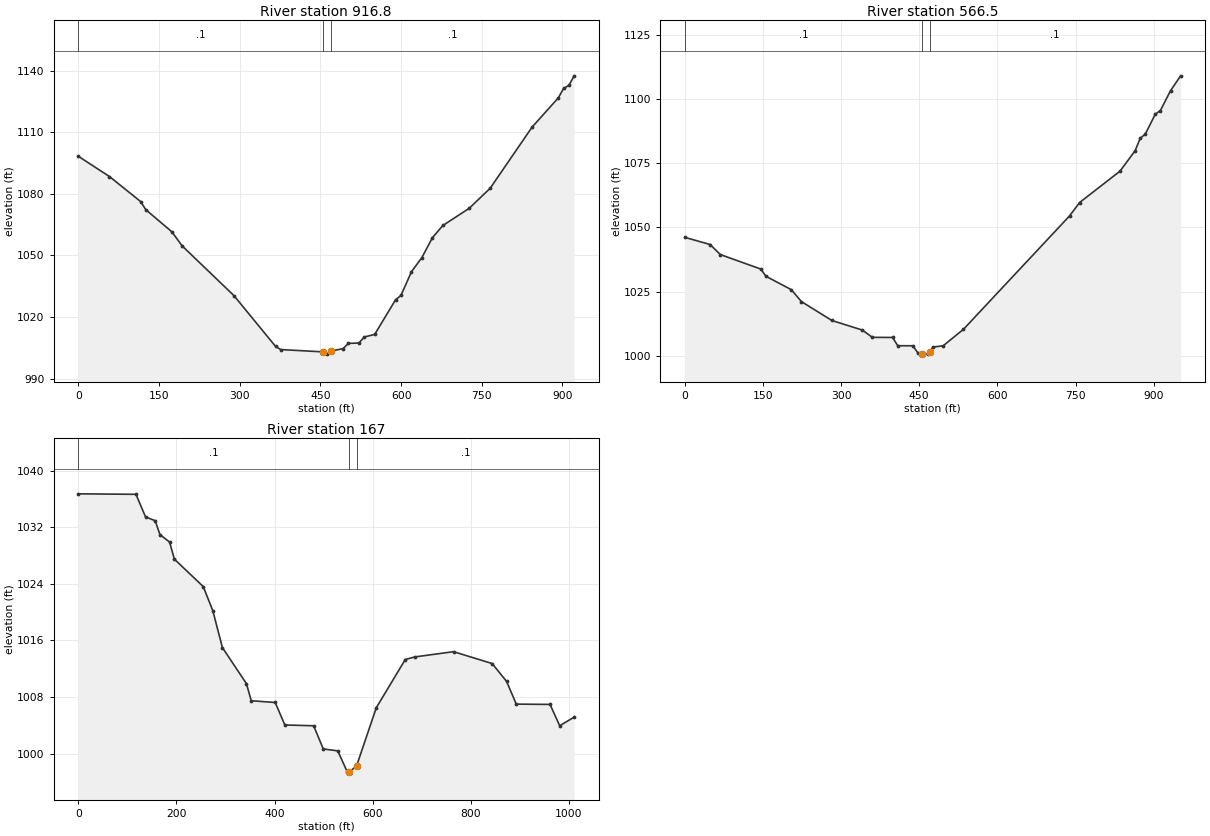
Type RM Length L Ch R = 1 ,916.8,351.655,350.365,351.73
XS GIS Cut Line= 3
     1712552.341      352614.218     1712090.690      352650.486
     1711640.302      352736.772
#Sta/Elev= 30
       0 1098.29    57.9 1088.43   115.8 1076.25   125.4 1072.29   173.7 1061.57
   192.9 1054.70   289.4 1030.42   366.6 1005.73   376.2 1004.19   455.6 1003.06
   463.1 1001.97   470.6 1003.49   492.3 1004.68   502.1 1007.22   521.6 1007.36
   531.4 1010.31   550.9 1011.56   589.9 1028.51   599.7 1030.52   619.2 1042.06
   638.7 1049.01   658.2 1058.65   677.7 1064.61   726.5 1072.94   765.5 1082.70
   843.6 1112.53   892.4 1126.78   902.1 1131.35   911.9 1132.80   921.7 1137.46
#Mann= 3 , 0 , 0
       0     0.1       0   455.6   0.045       0   470.6     0.1       0
Bank Sta=   455.6,   470.6
Exp/Cntr=0.3,0.1

Type RM Length L Ch R = 1 ,566.5,399.887,399.487,399.086
XS GIS Cut Line= 3
     1712580.967      352391.529     1712190.933      352307.197
     1711641.906      352371.395
#Sta/Elev= 30
       0 1046.15    48.7 1043.35    68.1 1039.46   146.0 1033.79   155.7 1031.00
   204.4 1025.78   223.9 1021.13   282.3 1013.78   340.6 1010.06   360.1 1007.22
   399.0 1007.17   408.7 1003.96   437.8 1003.93   447.5 1001.16   455.3 1000.88
   466.9 1000.68   470.3 1001.64   476.6 1003.43   496.0 1003.93   534.8 1010.32
   738.5 1054.47   757.9 1059.71   835.4 1071.91   864.5 1079.88   874.2 1084.69
   883.9 1086.34   903.3 1094.13   913.0 1095.52   932.4 1103.25   951.8 1109.03
#Mann= 3 , 0 , 0
       0     0.1       0   455.3   0.045       0   470.3     0.1       0
Bank Sta=   455.3,   470.3
Exp/Cntr=0.3,0.1

Type RM Length L Ch R = 1 ,167,167.789,166.97,166.151
XS GIS Cut Line= 3
     1712486.094      351822.290     1712009.019      351969.693
     1711502.258      352038.993
#Sta/Elev= 30
       0 1036.74   117.5 1036.67   137.1 1033.46   156.7 1032.94   166.4 1030.97
   186.0 1029.92   195.8 1027.50   254.6 1023.62   274.1 1020.22   293.7 1014.99
   342.7 1009.89   352.5 1007.47   401.4 1007.22   421.0 1004.04   479.7 1003.93
   499.3 1000.65   528.8 1000.38   548.5  997.37   552.4  997.37   567.4  998.28
   607.5 1006.49   666.5 1013.30   686.2 1013.67   764.9 1014.41   843.6 1012.73
   873.1 1010.20   892.8 1006.99   961.6 1006.95   981.3 1003.93  1010.8 1005.15
#Mann= 3 , 0 , 0
       0     0.1       0   552.4   0.045       0   567.4     0.1       0
Bank Sta=   552.4,   567.4
Exp/Cntr=0.3,0.1